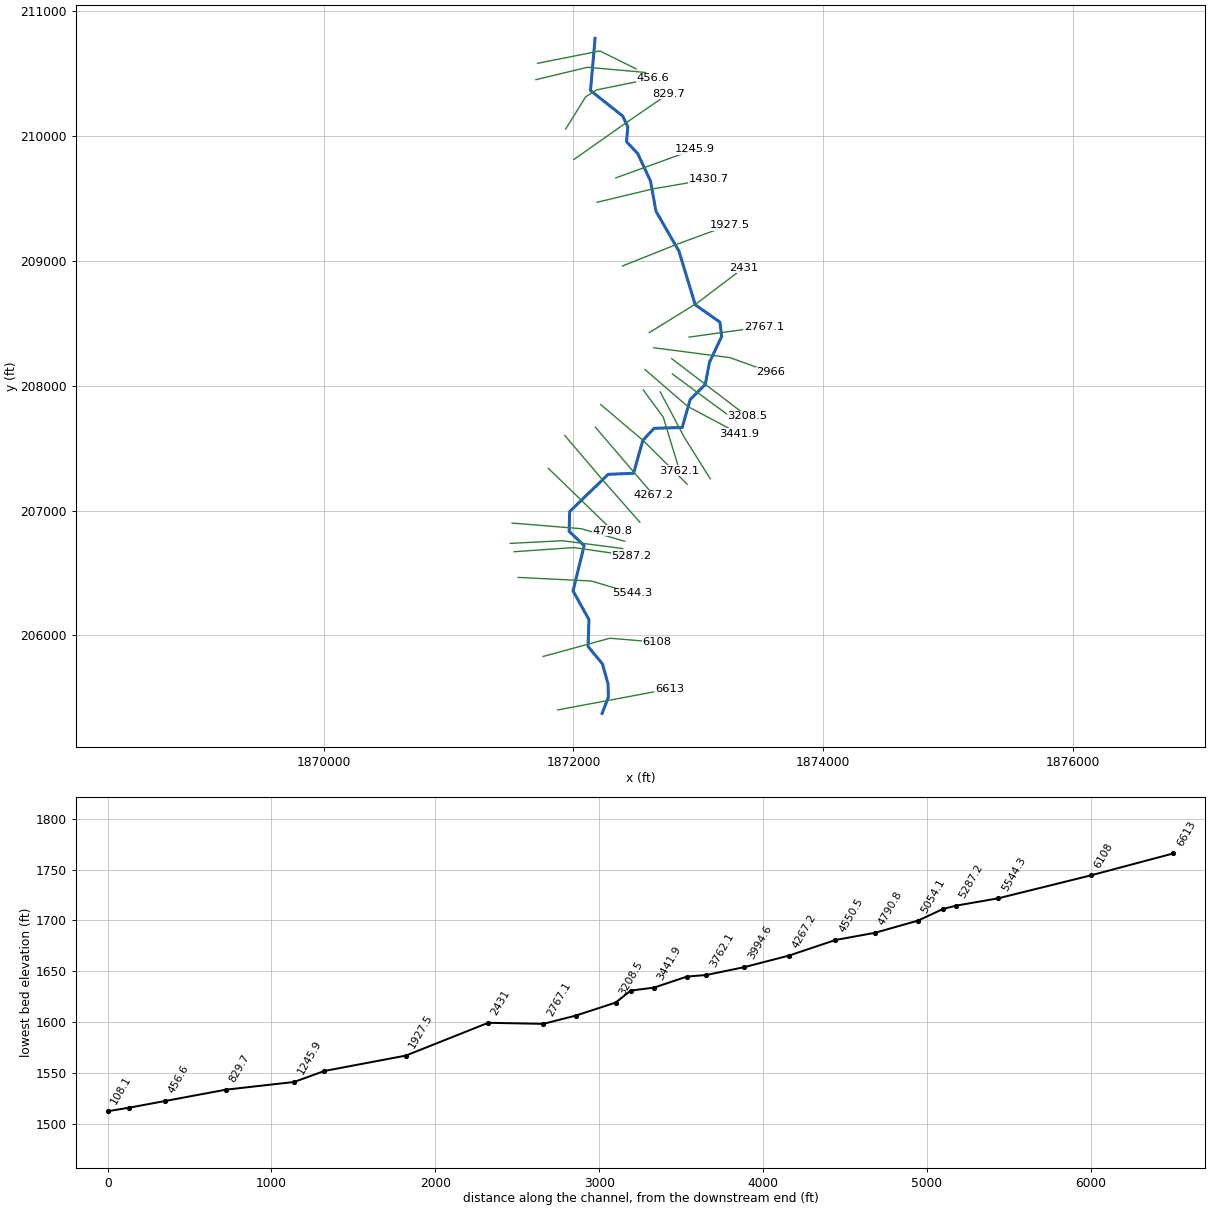
--- BigBr4.prj (project) ---

Proj Title=BigBr4
Current Plan=p01
Default Exp/Contr=0,0
English Units
Geom File=g01
Flow File=f01
Plan File=p01
BEGIN DESCRIPTION:
END DESCRIPTION:
DSS Export Rating Curves= 0
DSS Export Rating Curve Sorted= 0
DSS Export Volume Flow Curves= 0
DXF OffsetX= 0
DXF OffsetY= 0
DXF ScaleX= 0
DXF ScaleY= 0

--- BigBr4.p01 (plan) ---

Plan Title=Floodplain
Program Version=4.00
Geom File=g01
Flow File=f01
K Sum by GR=0
Std Step Tol=0.01
Critical Tol=0.01
Num of Std Step Trials=20
Max Error Tol=0.3
Flow Tol Ratio=0.001
Split Flow NTrial=30
Split Flow Tol=0.02
Split Flow Ratio=0.02
Log Output Level=0
Friction Slope Method=1
Unsteady Friction Slope Method=2
Unsteady Bridges Friction Slope Method=1
Global Log Level=0
CheckData=False
Run HTab=0
Run UNet=0
Run PostProcess=0
UNET Theta=0
UNET Theta Warmup=0
UNET ZTol=0
UNET ZSATol=0
UNET MxIter=0
UNET MaxInSteps=0
UNET DtIC=0
UNET DtMin=0
UNET MaxCRTS=0
UNET WFStab=0
UNET SFStab=0
UNET WFX=0
UNET SFX=0
UNET DSS MLevel=0
UNET DZMax Abort=0
UNET Convert EG Bridges=0
UNET Use Existing IB Tables=0
UNET Froude Limit=0
UNET Froude Power=0
Write IC File=0
Echo Input=False
Echo Output=False
Write Detailed=0

--- BigBr4.f01 (steady flow) ---

Flow Title=NFF Regression Equation
Program Version=4.00
Number of Profiles=1
Profile Names=P100yr
River Rch & RM=BigBr4,Main      ,6613
760.0131
River Rch & RM=BigBr4,Main      ,5054.1
782.4037
River Rch & RM=BigBr4,Main      ,4790.8
883.8782
River Rch & RM=BigBr4,Main      ,2431
961.8872
River Rch & RM=BigBr4,Main      ,1430.7
1049.457
River Rch & RM=BigBr4,Main      ,237.8
1147.127
Boundary for River Rch & Prof#=BigBr4,Main      ,1
Up Type=0
Dn Type=3
Dn Slope=0.029181

--- BigBr4.g01 (geometry) ---

Geom Title=USGS 10m DEM
Program Version=4.00

River Reach=BigBr4          ,Main
Reach XY= 30
     1872229.949      205375.692     1872280.092      205506.272
     1872276.958       205613.87     1872232.038      205772.656
     1872117.128      205911.593      1872124.44       206126.79
     1871996.994      206356.611     1872085.788      206719.102
     1871965.655      206834.012     1871969.833      206991.753
     1872278.002      207290.521     1872481.708      207298.878
     1872555.877      207562.128     1872646.761       207659.28
     1872871.359      207665.547     1872935.082      207889.101
     1873056.261      208010.279     1873089.689      208187.868
     1873187.886      208395.752     1873173.261      208509.618
     1872975.823      208648.555     1872845.243      209077.904
     1872661.386      209397.564     1872617.511      209639.921
     1872515.136      209859.296     1872425.297      209955.403
     1872435.744      210073.448     1872395.003      210160.153
     1872136.648      210364.546     1872173.538       210782.76

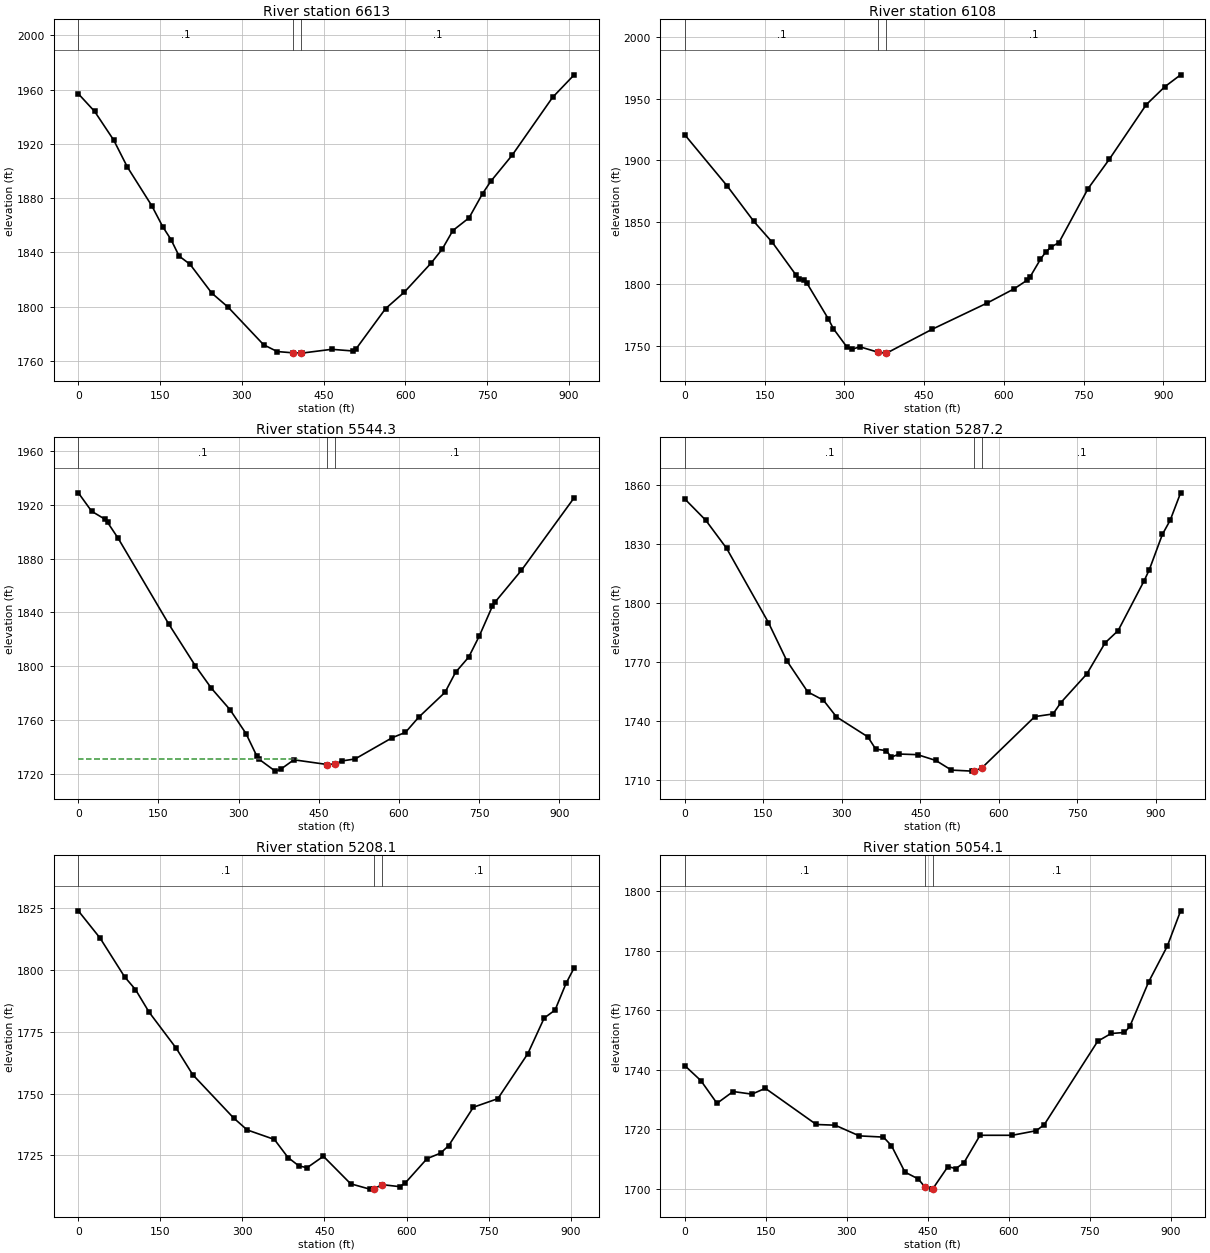
Type RM Length L Ch R = 1 ,6613    ,504.2,505,505.7
XS GIS Cut Line= 3
      1871875.01      205403.461     1872322.204      205487.384
     1872769.397      205571.308
#Sta/Elev= 30
       0 1956.87      30 1943.82      65 1922.69      90  1902.9     135 1874.26
     155 1858.88     170 1849.52     185 1837.31     205 1831.26     245    1810
     275 1799.63     340    1772     365 1766.98   393.4 1766.06   408.4 1765.84
     410 1765.82   464.9 1768.63   504.5 1767.39   509.4 1768.78   563.8 1798.57
   598.4 1810.78   647.9 1832.34   667.7 1842.34   687.4 1856.13   717.1 1865.47
   741.8 1883.24   756.7 1892.25   796.2 1911.61   870.4 1954.22     910 1970.83
#Mann= 3 , 0 , 0
       0      .1       0   393.4    .045       0   408.4      .1       0
Bank Sta=393.4,408.4
XS Rating Curve= 0 ,0
Exp/Cntr=0.3,0.1

Type RM Length L Ch R = 1 ,6108    ,571.3,563.7,556.1
XS GIS Cut Line= 3
     1871757.624      205831.499     1872292.098      205977.597
     1872668.893      205946.115
#Sta/Elev= 30
       0  1920.7    79.9 1879.24   129.8  1850.7   164.7 1833.69   209.6 1807.04
   214.6 1804.43   224.6 1803.15   229.6  1800.8   269.6  1772.1   279.5  1763.9
   304.5 1749.33   314.5  1747.4   329.4 1749.32   363.9 1744.89   378.9 1744.24
   379.4 1744.23   464.2 1763.34     569 1784.84   618.8 1796.12   643.6 1803.17
   648.6 1805.42   668.5 1819.96   678.5  1825.9   688.4 1829.95   703.3 1833.51
   758.1 1877.15   797.9 1900.79   867.5 1945.03   902.3  1959.5   932.2 1969.18
#Mann= 3 , 0 , 0
       0      .1       0   363.9    .045       0   378.9      .1       0
Bank Sta=363.9,378.9
XS Rating Curve= 0 ,0
Exp/Cntr=0.3,0.1

Type RM Length L Ch R = 1 ,5544.3  ,259.4,257.1,254.8
XS GIS Cut Line= 3
      1871557.25      206464.762     1872144.212      206436.009
     1872470.166      206338.299
#Sta/Elev= 30
       0  1929.1    24.9 1915.37    49.8 1909.45    54.8 1907.04    74.7 1895.13
   169.3 1831.32   219.1 1800.19     249 1783.53   283.9 1767.55   313.8 1749.78
   333.7 1733.29   338.6 1730.53   368.5 1721.78   378.5 1723.11   403.4 1730.22
   466.2 1726.69   481.2 1727.19     493 1729.35   517.9 1730.83   587.7 1746.72
   612.3 1750.67     637 1761.92   686.3 1780.47     706 1795.37   730.7 1806.76
   750.4 1822.38   775.1 1844.77     780 1847.71   829.3 1871.39     928 1925.42
#Mann= 3 , 0 , 0
       0      .1       0   466.2    .045       0   481.2      .1       0
#XS Ineff= 2 , 0
          408.63 1730.45
Permanent Ineff=
       F       F
Bank Sta=466.2,481.2
XS Rating Curve= 0 ,0
Exp/Cntr=0.3,0.1

Type RM Length L Ch R = 1 ,5287.2  ,98.5,79.1,45.4
XS GIS Cut Line= 3
     1871524.703      206670.449     1872003.051      206703.776
     1872465.715      206637.121
#Sta/Elev= 30
       0 1852.96      40 1842.15    79.9 1827.84   159.8 1790.09   194.8 1770.72
   234.8 1754.86   264.7 1750.65   289.7 1742.16   349.6 1732.01   364.6 1725.77
   384.6 1725.01   394.6 1721.71   409.6 1723.27   444.5 1722.95   479.5    1720
   509.3  1715.1   549.1 1714.58   552.8 1714.64   567.8 1716.31   668.5  1742.3
   703.3 1743.65   718.2 1749.41   767.9 1764.01   802.7 1779.78   827.6 1786.02
   877.3 1811.36   887.3 1817.06   912.1 1834.91   927.1 1842.16     947 1856.08
#Mann= 3 , 0 , 0
       0      .1       0   552.8    .045       0   567.8      .1       0
Bank Sta=552.8,567.8
XS Rating Curve= 0 ,0
Exp/Cntr=0.3,0.1

Type RM Length L Ch R = 1 ,5208.1  ,148.5,154,190.8
XS GIS Cut Line= 3
     1871493.335      206737.104      1871910.91      206758.669
     1872395.139      206695.935
#Sta/Elev= 30
       0 1823.76    39.8 1812.74    84.6 1797.11   104.5 1791.96   129.4 1782.83
   179.2  1768.2   209.1 1757.61   283.7 1740.16   308.6  1735.3   358.4 1731.45
   383.3 1724.15   403.2 1720.77   418.1 1720.03     448 1724.65   497.8 1713.55
   532.7 1711.39   540.8 1711.61   555.8 1713.19   587.5 1712.39   597.5 1713.84
   637.4 1723.69   662.3 1725.94   677.2    1729   722.1 1744.45   766.9 1747.92
   821.7 1766.09   851.6 1780.47   871.5 1783.69   891.5 1794.43   906.4 1800.74
#Mann= 3 , 0 , 0
       0      .1       0   540.8    .045       0   555.8      .1       0
Bank Sta=540.8,555.8
XS Rating Curve= 0 ,0
Exp/Cntr=0.3,0.1

Type RM Length L Ch R = 1 ,5054.1  ,278.8,263.3,247.7
XS GIS Cut Line= 3
     1871509.017      206900.084     1872063.824       206854.73
     1872411.018      206754.171
#Sta/Elev= 30
       0 1741.41    29.8 1736.36    59.6 1728.73    89.5  1732.7   124.2 1731.82
   149.1 1733.78   243.5 1721.61   278.3 1721.38   323.1 1717.78   367.8 1717.37
   382.7 1714.48   407.6  1705.6   432.4 1703.29   444.5 1700.59   457.2 1699.87
   459.5 1700.07   487.1 1707.42     502 1706.79   516.9 1708.75   546.7 1717.98
   606.2 1717.98   650.7 1719.52   665.6 1721.56   764.6 1749.62   789.4 1752.22
   814.1 1752.56     824 1754.58   858.7  1769.5   893.4 1781.59   918.1 1793.48
#Mann= 3 , 0 , 0
       0      .1       0   444.5    .045       0   459.5      .1       0
Bank Sta=444.5,459.5
XS Rating Curve= 0 ,0
Exp/Cntr=0.3,0.1

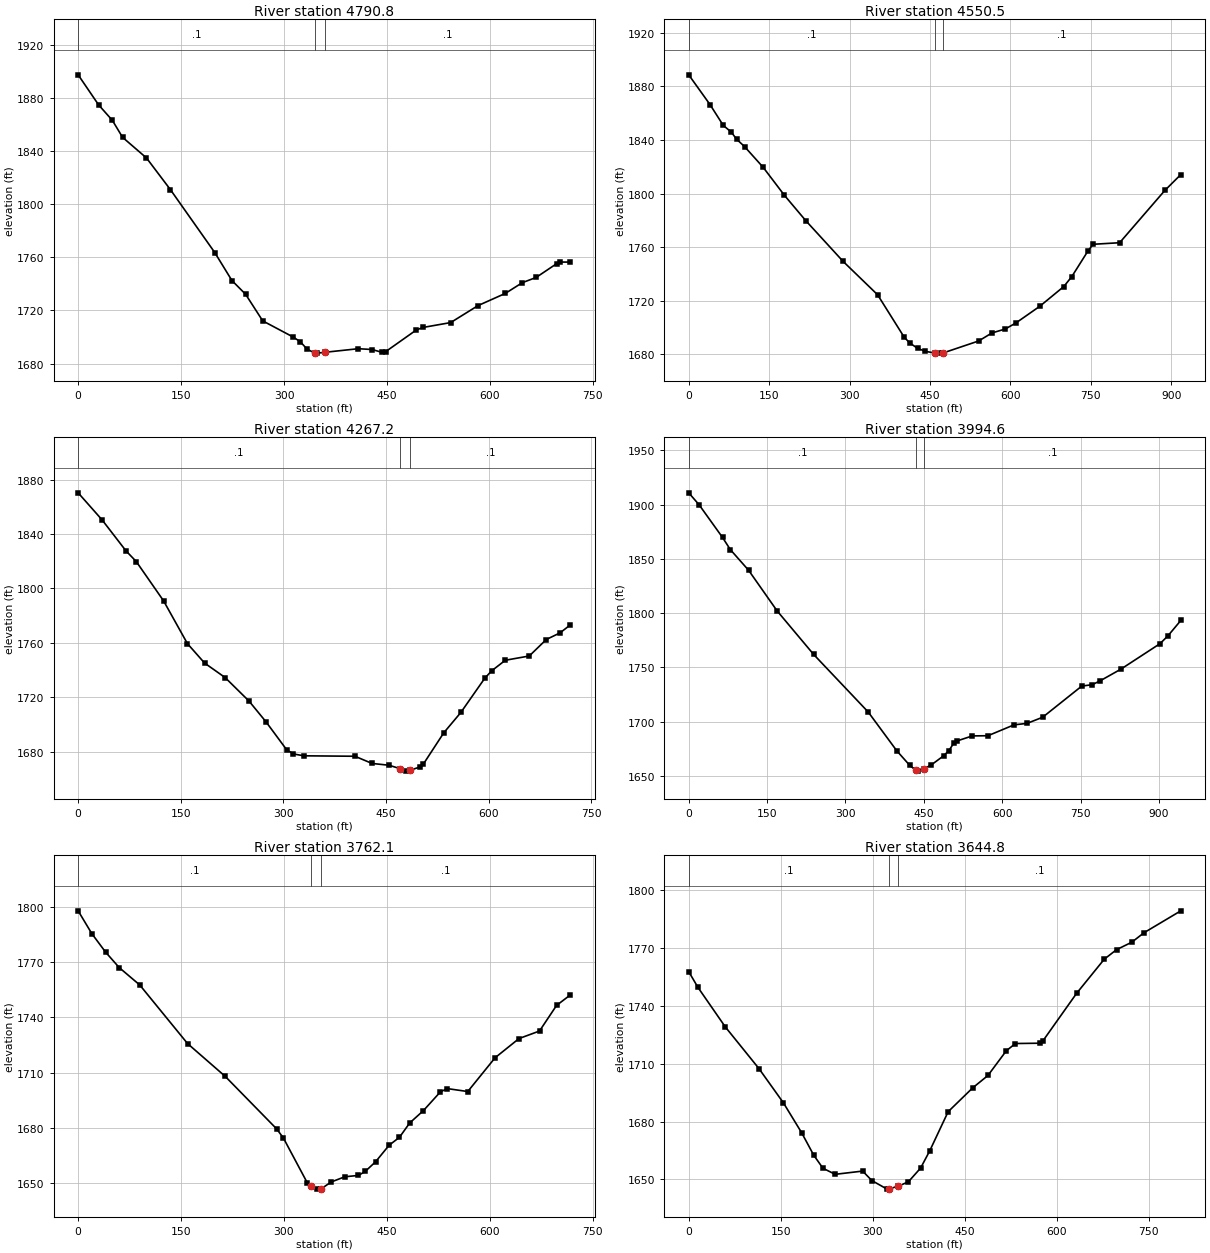
Type RM Length L Ch R = 1 ,4790.8  ,242.7,240.4,238.4
XS GIS Cut Line= 2
     1871799.164      207338.633     1872314.108      206839.374
#Sta/Elev= 30
       0 1897.44    29.9 1874.76    49.8  1863.2    64.8 1850.36    99.6 1834.84
   134.5 1810.97   199.2 1763.55   224.1 1742.56   244.1 1732.17     269 1712.17
   313.8 1699.88   323.8 1696.42   333.7 1690.88   344.6 1687.99   348.7 1687.88
   359.6 1688.51   408.4 1691.21   428.4  1690.6   443.3 1688.42   448.3 1689.03
   493.1  1705.4   503.1 1707.26   542.9 1710.88   582.8 1723.67   622.6 1732.85
   647.5 1740.97   667.4 1744.84   697.3 1755.21   702.3 1756.46   717.2 1756.43
#Mann= 3 , 0 , 0
       0      .1       0   344.6    .045       0   359.6      .1       0
Bank Sta=344.6,359.6
XS Rating Curve= 0 ,0
Exp/Cntr=0.3,0.1

Type RM Length L Ch R = 1 ,4550.5  ,282.5,283.3,283.8
XS GIS Cut Line= 3
      1871931.64      207600.951     1872230.708       207249.49
     1872532.322      206906.762
#Sta/Elev= 30
       0 1888.62    39.7 1866.42    64.5 1850.84    79.4 1845.88    89.3 1840.56
   104.2 1835.02   138.9 1819.56   178.6 1798.64   218.3 1779.78   287.8 1749.42
   352.3 1724.45   401.9 1692.79   411.9  1688.6   426.8 1684.44   441.6 1682.14
   459.1    1681   471.4 1680.85   474.1 1680.92   540.9 1689.93   565.7 1695.92
   590.5 1698.86   610.4 1703.38     655 1715.85   699.7 1730.56   714.6 1737.95
   744.3 1756.81   754.3 1762.11   803.9 1763.28   888.2  1802.3     918 1814.16
#Mann= 3 , 0 , 0
       0      .1       0   459.1    .045       0   474.1      .1       0
Bank Sta=459.1,474.1
XS Rating Curve= 0 ,0
Exp/Cntr=0.3,0.1

Type RM Length L Ch R = 1 ,4267.2  ,268.9,272.6,274.2
XS GIS Cut Line= 2
      1872175.57      207667.987     1872643.462      207121.677
#Sta/Elev= 30
       0 1870.28      35 1850.38    69.9 1827.61    84.9 1819.76   124.9  1790.8
   159.8 1759.31   184.8 1745.07   214.8 1734.42   249.8 1717.08   274.7 1701.77
   304.7 1681.35   314.7 1678.22   329.7 1676.84   404.6 1676.51   429.6 1671.22
   454.6 1669.89   470.6 1667.37   479.5 1665.57   485.6 1666.28   499.5 1668.61
   504.5 1670.66   534.5  1693.8   559.4 1708.72   594.4 1733.91   604.4 1739.32
   624.4 1747.13   659.4 1750.26   684.3 1762.39   704.3 1767.24   719.3 1773.08
#Mann= 3 , 0 , 0
       0      .1       0   470.6    .045       0   485.6      .1       0
Bank Sta=470.6,485.6
XS Rating Curve= 0 ,0
Exp/Cntr=0.3,0.1

Type RM Length L Ch R = 1 ,3994.6  ,245.6,232.5,223.6
XS GIS Cut Line= 3
     1872218.758      207848.883     1872560.806      207559.341
     1872911.252      207211.366
#Sta/Elev= 30
       0 1910.92    19.9 1899.87    64.7 1869.77    79.7 1858.53   114.5 1839.58
   169.3 1801.98     239 1761.94   343.6 1708.76   398.4 1672.94   423.2 1659.51
   434.9 1654.92   438.2 1654.24   449.9 1656.56   463.1 1659.52     488 1668.39
     498 1673.21     508 1680.44     513 1681.98   542.9 1686.72   572.8 1686.89
   622.7 1696.92   647.7 1698.28   677.6 1703.95   752.4 1732.68   772.4 1733.95
   787.4 1737.48   827.3 1748.29   902.1 1771.77   917.1 1778.87     942  1793.2
#Mann= 3 , 0 , 0
       0      .1       0   434.9    .045       0   449.9      .1       0
Bank Sta=434.9,449.9
XS Rating Curve= 0 ,0
Exp/Cntr=0.3,0.1

Type RM Length L Ch R = 1 ,3762.1  ,113,117.3,119.4
XS GIS Cut Line= 3
     1872559.816      207965.975     1872719.266      207749.019
     1872849.962      207320.336
#Sta/Elev= 30
       0 1798.06    19.9 1785.66    39.9 1775.62    59.8 1767.17    89.8 1757.68
   159.6 1725.73   214.4  1707.9   289.2 1679.36   299.1 1674.42     334 1649.97
   339.7 1648.18   348.9 1646.49   354.7 1646.76   368.8 1650.36   388.8 1653.23
   408.7 1653.95   418.6 1656.17   433.6 1661.38   453.5 1670.45   468.4  1674.7
   483.4 1682.54   503.3 1689.23   528.2 1699.49   538.2 1701.24     568 1699.64
   607.9 1718.06   642.7 1728.49   672.6  1732.6   697.5 1746.56   717.4 1752.21
#Mann= 3 , 0 , 0
       0      .1       0   339.7    .045       0   354.7      .1       0
Bank Sta=339.7,354.7
XS Rating Curve= 0 ,0
Exp/Cntr=0.3,0.1

Type RM Length L Ch R = 1 ,3644.8  ,195.3,202.9,216.3
XS GIS Cut Line= 3
      1872695.74      207950.291     1872886.557       207589.57
     1873095.671      207254.988
#Sta/Elev= 30
       0 1757.79    14.9 1749.68    59.7  1729.1   114.5 1707.51   154.3 1689.79
   184.1 1674.27     204 1662.51     219 1655.78   238.9 1652.65   283.7 1654.33
   298.6 1649.44   323.5 1644.97   326.8 1645.11   341.8  1646.5   358.3 1648.78
   378.2 1655.89   393.2  1664.9   423.1 1685.12     463 1697.45     488 1703.91
     518 1716.74   532.9 1720.49   572.9 1720.66   577.9 1721.96   632.8  1746.6
   677.8 1764.25   697.8 1769.18   722.7 1773.05   742.7 1777.98   802.6 1789.32
#Mann= 3 , 0 , 0
       0      .1       0   326.8    .045       0   341.8      .1       0
Bank Sta=326.8,341.8
XS Rating Curve= 0 ,0
Exp/Cntr=0.3,0.1

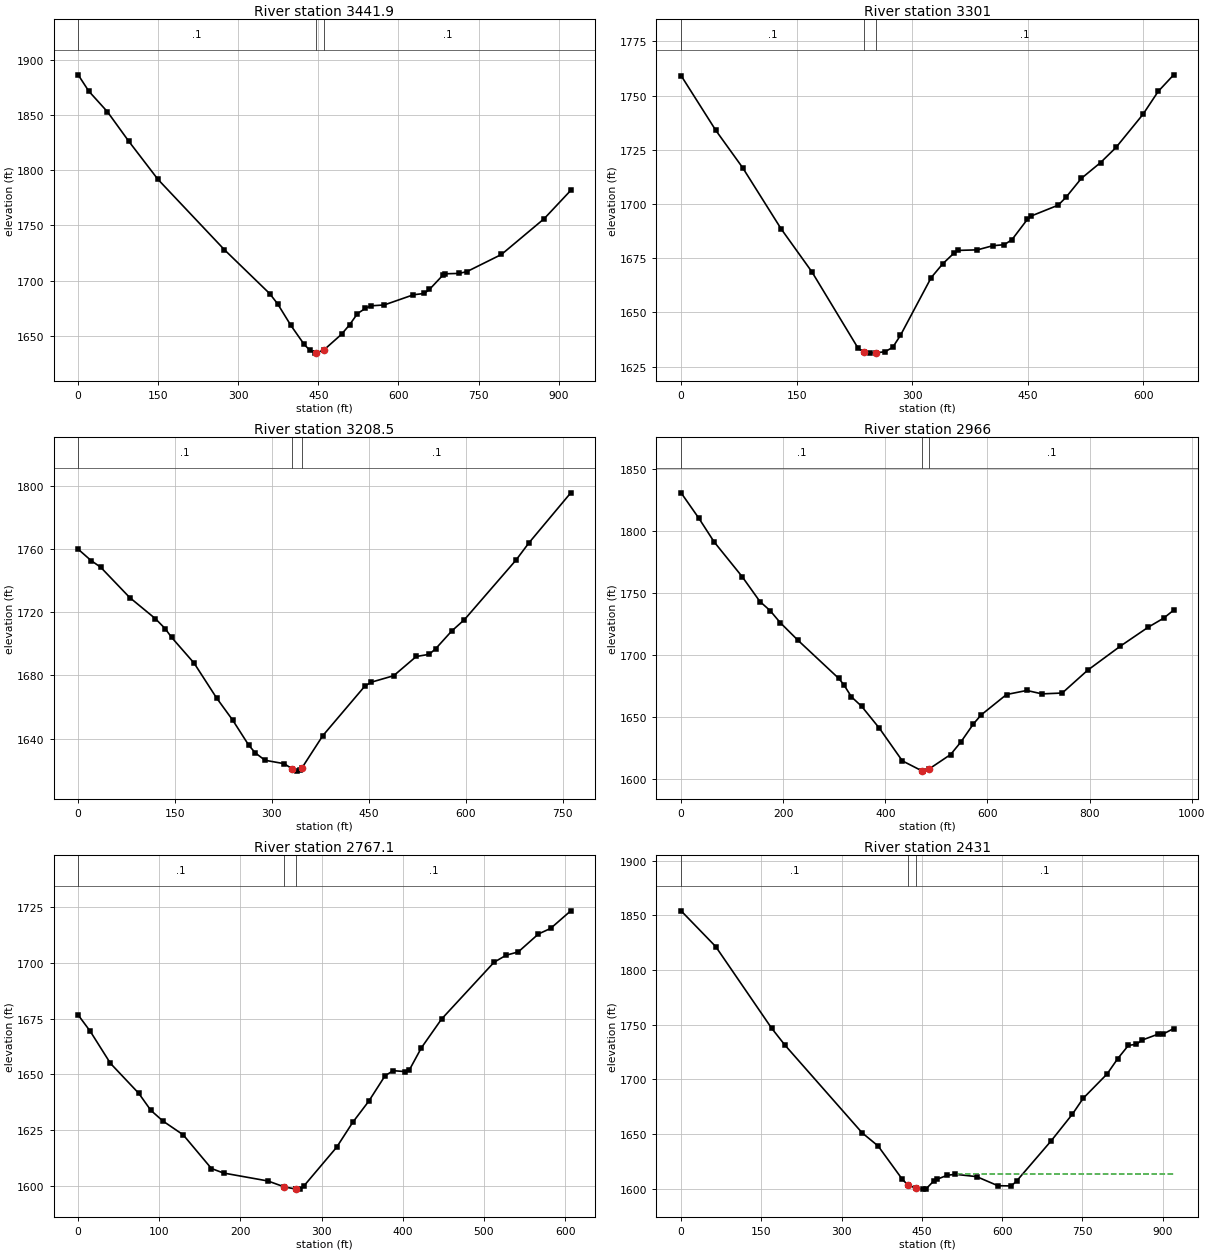
Type RM Length L Ch R = 1 ,3441.9  ,138,140.9,138
XS GIS Cut Line= 3
     1872572.061      208130.793     1872915.117      207834.448
     1873329.633      207614.256
#Sta/Elev= 30
       0 1886.71    19.9 1871.87    54.8 1853.18    94.6 1826.51   149.4 1791.83
     274  1727.9   358.7 1688.12   373.6 1678.82   398.5 1659.19   423.4 1641.93
   433.4 1636.98   443.4 1634.09   445.9 1634.11   460.9 1637.25   493.3  1651.2
   508.3 1659.75   523.2 1669.99   538.2  1674.8   548.2 1677.04   573.2  1677.8
   628.1 1687.08   648.1 1688.24     658  1691.9     683 1704.78     688 1706.11
     713 1706.44     728 1708.04   792.9 1723.66   872.8 1756.08   922.7 1781.82
#Mann= 3 , 0 , 0
       0      .1       0   445.9    .045       0   460.9      .1       0
Bank Sta=445.9,460.9
XS Rating Curve= 0 ,0
Exp/Cntr=0.3,0.1

Type RM Length L Ch R = 1 ,3301    ,93.4,92.4,91.6
XS GIS Cut Line= 2
     1872792.456      208094.057     1873307.399      207715.038
#Sta/Elev= 30
       0  1759.2      45 1733.97    79.9 1716.74   129.9 1688.49   169.8  1668.7
   229.8 1633.46   237.7 1631.59   244.8 1631.22   252.7 1631.35   264.8 1631.88
   274.7 1633.89   284.7 1639.39   324.7 1666.08   339.7 1672.43   354.7 1677.51
   359.7 1678.59   384.6 1678.84   404.6 1680.75   419.6 1681.23   429.6 1683.59
   449.6 1692.96   454.6 1694.47   489.5 1699.45   499.5 1703.03   519.5 1711.78
   544.5 1719.09   564.5 1726.04   599.4 1741.26   619.4 1751.95   639.4 1759.55
#Mann= 3 , 0 , 0
       0      .1       0   237.7    .045       0   252.7      .1       0
Bank Sta=237.7,252.7
XS Rating Curve= 0 ,0
Exp/Cntr=0.3,0.1

Type RM Length L Ch R = 1 ,3208.5  ,230.4,242.6,254.5
XS GIS Cut Line= 2
     1872787.228      208216.911     1873393.658      207754.247
#Sta/Elev= 30
       0 1759.75    19.9 1752.61    34.9 1748.33    79.8 1729.18   119.6 1715.81
   134.6 1709.58   144.6 1704.04   179.5 1687.73   214.4 1665.65   239.3 1651.67
   264.2 1635.79   274.2    1631   289.2 1626.31   319.1 1624.13   331.3 1620.89
     339 1619.43     344 1619.94   346.3 1621.33   378.9  1641.9   443.7 1673.07
   453.7 1675.64   488.6 1679.76   523.5 1691.91   543.4 1693.27   553.4 1696.73
   578.3 1707.96   598.2 1715.24     678 1752.87     698 1763.75   762.8  1795.4
#Mann= 3 , 0 , 0
       0      .1       0   331.3    .045       0   346.3      .1       0
Bank Sta=331.3,346.3
XS Rating Curve= 0 ,0
Exp/Cntr=0.3,0.1

Type RM Length L Ch R = 1 ,2966    ,192.7,198.8,205
XS GIS Cut Line= 3
      1872642.75      208304.595      1873255.12      208224.753
     1873581.861      208107.127
#Sta/Elev= 30
       0 1830.94    34.9  1810.4    64.7  1791.4   119.5 1763.46   154.4 1743.35
   174.3 1736.06   194.2 1726.32   229.1 1712.05   308.8  1681.4   318.7 1676.32
   333.7 1666.51   353.6 1658.93   388.5 1641.19   433.3 1614.98   471.2 1607.01
   473.1 1606.69   486.2 1608.56   527.9 1620.08   547.8 1630.05   572.7  1644.8
   587.7 1651.96   637.4 1668.42   677.1 1671.69   706.8 1668.93   746.5 1669.62
   796.2 1687.96   860.6 1707.46   915.2 1722.74     945  1729.9   964.8  1736.4
#Mann= 3 , 0 , 0
       0      .1       0   471.2    .045       0   486.2      .1       0
Bank Sta=471.2,486.2
XS Rating Curve= 0 ,0
Exp/Cntr=0.3,0.1

Type RM Length L Ch R = 1 ,2767.1  ,326.5,336.1,345.8
XS GIS Cut Line= 2
     1872925.766       208389.43     1873526.968      208473.076
#Sta/Elev= 30
       0 1676.66    14.9 1669.34    39.8 1654.95    74.6 1641.54    89.6 1633.86
   104.5 1629.07   129.4  1622.9   164.2 1607.78   179.1 1605.75   233.8 1602.19
   253.8 1599.55   268.7 1598.53   268.8 1598.54   273.6 1598.72   278.6 1600.14
   318.4 1617.28   338.3 1628.48   358.2 1638.04   378.1 1649.36   388.1 1651.69
     403 1651.26     408 1651.93   422.9 1661.93   447.8 1674.84   512.5 1700.34
   527.4 1703.49   542.3 1704.96   567.2 1713.03   582.1 1715.49     607  1723.4
#Mann= 3 , 0 , 0
       0      .1       0   253.8    .045       0   268.8      .1       0
Bank Sta=253.8,268.8
XS Rating Curve= 0 ,0
Exp/Cntr=0.3,0.1

Type RM Length L Ch R = 1 ,2431    ,507.4,503.5,498.9
XS GIS Cut Line= 3
     1872607.975      208425.827     1872993.169       208663.74
     1873366.127      208946.098
#Sta/Elev= 30
       0 1854.16    64.7 1821.46   169.2  1746.8     194 1731.37   338.3  1651.1
   368.2 1639.04   412.9 1608.93   423.1 1603.67   438.1 1600.51   452.7  1599.6
   457.7 1599.81   472.6 1607.28   477.6  1608.5   497.5 1612.29   512.5 1613.16
   552.3 1611.03   592.1  1602.7     617 1602.53   626.9 1606.95   691.6 1643.79
   731.4 1668.27   751.3 1682.63   796.1 1704.97     816    1719   835.9 1731.11
   850.9 1732.04   860.8 1735.81   890.7 1741.23   900.6 1741.47   920.5 1746.46
#Mann= 3 , 0 , 0
       0      .1       0   423.1    .045       0   438.1      .1       0
#XS Ineff= 2 , 0
                          516.76         1613.02
Permanent Ineff=
       F       F
Bank Sta=423.1,438.1
XS Rating Curve= 0 ,0
Exp/Cntr=0.3,0.1

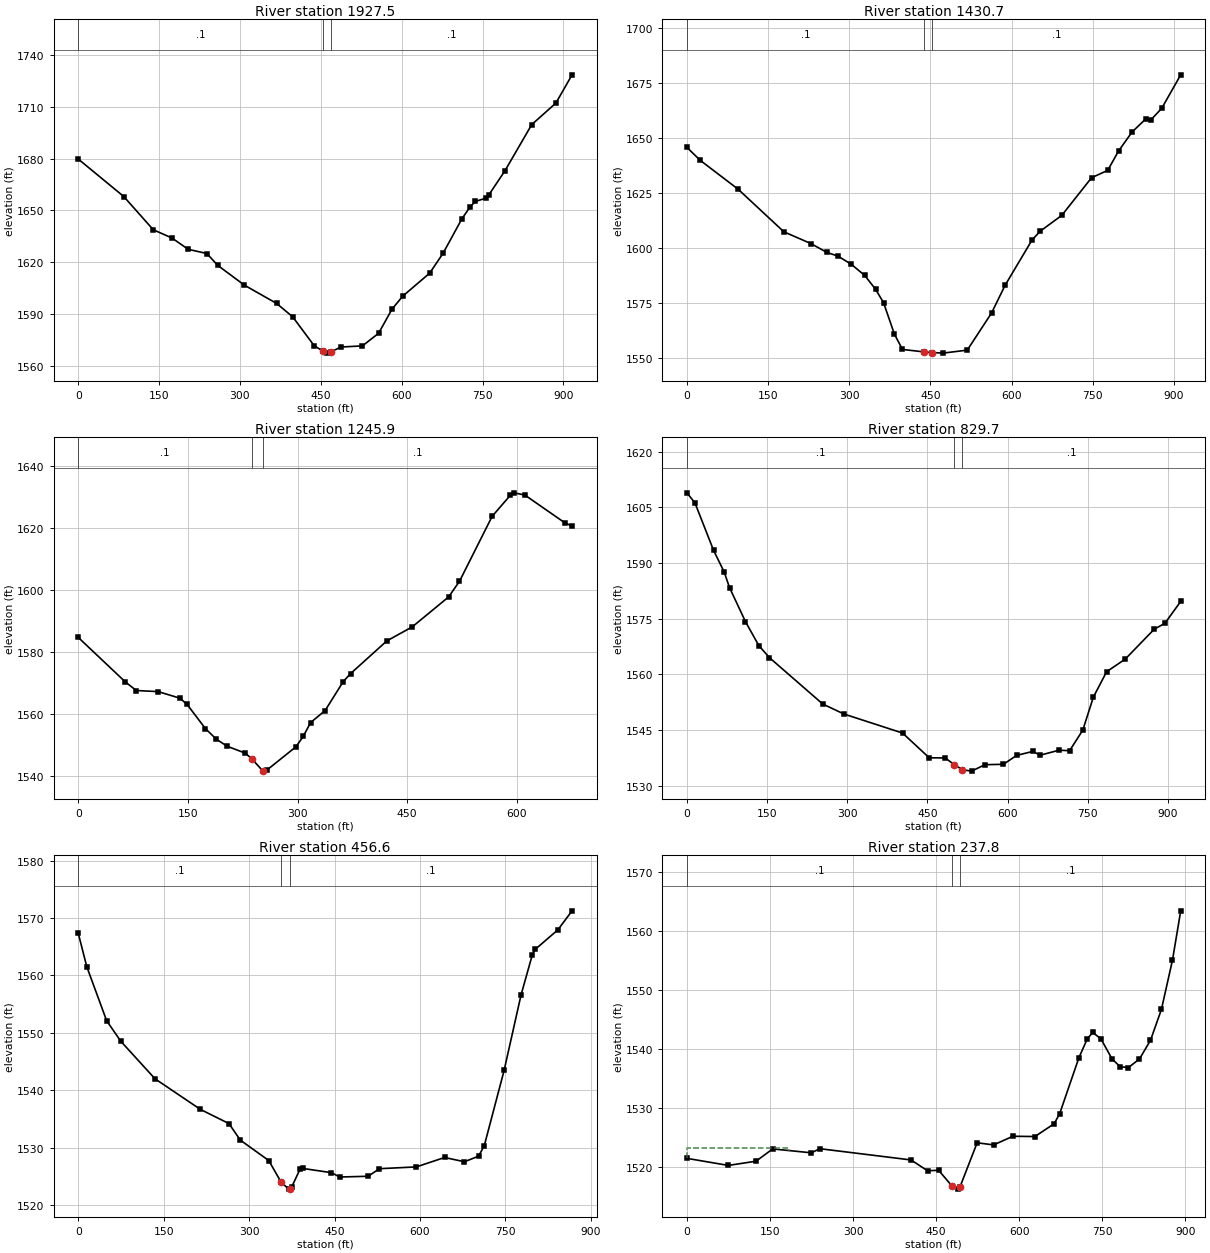
Type RM Length L Ch R = 1 ,1927.5  ,500.1,496.8,493.5
XS GIS Cut Line= 3
     1872394.314      208959.609     1872823.716      209131.262
     1873249.554      209287.766
#Sta/Elev= 30
       0 1679.81    84.5 1658.09   139.2 1638.85     174 1634.04   203.9 1627.53
   238.7 1625.07   258.6 1618.26   308.3 1606.74     368 1596.17   397.8 1588.42
   437.6 1571.72   453.4 1568.62   462.4 1567.38   468.4 1568.06   487.4 1570.92
   527.2 1571.57   557.2 1578.86   582.1 1592.85     602 1600.39   651.9 1613.68
   676.8  1625.2   711.7 1645.15   726.7 1651.97   736.6 1655.24   756.6 1657.18
   761.6 1658.98   791.5 1672.95   841.3 1699.75   886.2 1712.26   916.1 1728.59
#Mann= 3 , 0 , 0
       0      .1       0   453.4    .045       0   468.4      .1       0
Bank Sta=453.4,468.4
XS Rating Curve= 0 ,0
Exp/Cntr=0.3,0.1

Type RM Length L Ch R = 1 ,1430.7  ,182.2,184.8,188.1
XS GIS Cut Line= 3
     1872189.245      209469.513     1872634.623      209576.394
     1873082.583      209653.019
#Sta/Elev= 30
       0 1645.71    24.9 1639.76    94.6 1626.72   179.2 1607.37     229 1602.05
   258.9 1597.99   278.8 1596.38   303.7 1592.65   328.6 1587.55   348.5 1581.33
   363.4 1575.19   383.4 1560.93   398.3 1553.98   438.7 1552.83   453.7 1552.57
     473  1552.3     518 1553.66   562.9 1570.49   587.9 1583.07   637.8 1603.68
   652.8 1607.65   692.8 1614.85   747.7 1631.92   777.6 1635.27   797.6 1644.06
   822.6 1652.69   847.6 1658.56   857.6 1658.23   877.5 1663.49   912.5 1678.64
#Mann= 3 , 0 , 0
       0      .1       0   438.7    .045       0   453.7      .1       0
Bank Sta=438.7,453.7
XS Rating Curve= 0 ,0
Exp/Cntr=0.3,0.1

Type RM Length L Ch R = 1 ,1245.9  ,424,416.3,422.2
XS GIS Cut Line= 2
     1872340.247      209665.025      1872975.43      209895.051
#Sta/Elev= 30
       0 1584.67    64.6 1570.26    79.5 1567.52   109.3 1567.17   139.1 1565.05
     149 1563.01   173.9 1555.26   188.8 1551.84   203.7 1549.54   228.5 1547.31
   237.1 1545.56   252.1 1541.68   253.3  1541.5   258.3 1541.88     298 1549.39
     308 1552.78   317.9 1557.17   337.8 1561.07   362.6 1570.42   372.6 1572.98
   422.2 1583.54     457 1588.07   506.7 1597.73   521.6 1602.78   566.3 1623.76
   591.1 1630.53   596.1 1631.34     611 1630.63   665.6 1621.68   675.6 1620.61
#Mann= 3 , 0 , 0
       0      .1       0   237.1    .045       0   252.1      .1       0
Bank Sta=237.1,252.1
XS Rating Curve= 0 ,0
Exp/Cntr=0.3,0.1

Type RM Length L Ch R = 1 ,829.7   ,374.1,373,372
XS GIS Cut Line= 3
     1872004.938      209812.841     1872387.745       210082.56
     1872763.329      210340.394
#Sta/Elev= 30
       0 1608.89      15  1606.2    49.8 1593.43    69.7 1587.58    79.7 1583.38
   109.6  1574.2   134.5 1567.77   154.4 1564.51   254.1 1552.03   293.9 1549.33
   403.5 1544.21   453.3 1537.55   483.1 1537.52   500.3 1535.69   515.3 1534.34
   532.7 1533.96   557.4 1535.69   592.1  1535.8   616.8 1538.19   646.6 1539.25
   661.4 1538.27   696.1 1539.59   715.9 1539.46   740.6    1545   760.4  1553.9
   785.2 1560.73   819.9 1564.11   874.3 1572.18   894.1 1573.75   923.8 1579.65
#Mann= 3 , 0 , 0
       0      .1       0   500.3    .045       0   515.3      .1       0
Bank Sta=500.3,515.3
XS Rating Curve= 0 ,0
Exp/Cntr=0.3,0.1

Type RM Length L Ch R = 1 ,456.6   ,233.2,218.9,204.2
XS GIS Cut Line= 4
     1871937.325      210055.248     1872097.814      210313.997
     1872186.866      210369.629     1872634.965      210461.386
#Sta/Elev= 30
       0 1567.37      15 1561.53    49.9 1552.11    74.9 1548.52   134.8    1542
   214.6 1536.66   264.6  1534.2   284.5 1531.32   334.5 1527.76     356 1524.02
   369.5 1522.78     371 1522.88   374.5  1523.1   389.5 1526.28   394.5 1526.38
   444.3 1525.65   459.2 1524.89   508.9 1525.02   528.8 1526.34   593.4 1526.65
   643.2 1528.29     678 1527.55   702.8 1528.52   712.8 1530.34   747.6 1543.45
   777.4 1556.62   797.3 1563.65   802.2 1564.54     842 1567.95   866.9 1571.26
#Mann= 3 , 0 , 0
       0      .1       0     356    .045       0     371      .1       0
Bank Sta=356,371
XS Rating Curve= 0 ,0
Exp/Cntr=0.3,0.1

Type RM Length L Ch R = 1 ,237.8   ,123.6,129.7,136
XS GIS Cut Line= 3
     1871699.836      210451.816     1872112.835      210551.145
     1872578.114      210509.323
#Sta/Elev= 30
       0 1521.45      75 1520.25   124.9 1520.97   154.9 1523.05   224.9 1522.39
   239.9 1523.09   404.8 1521.18   434.7 1519.34   454.6 1519.43   478.3 1516.81
   489.4 1516.23   493.3 1516.63   524.2 1524.09     554 1523.73   588.8  1525.2
   628.5 1525.15   663.3 1527.32   673.3 1529.04     708 1538.52     723 1541.69
   732.9 1542.81   747.8 1541.72   767.7 1538.34   782.6 1536.98   797.5 1536.86
   817.4 1538.31   837.3 1541.47   857.1 1546.74     877 1555.08   891.9 1563.44
#Mann= 3 , 0 , 0
       0      .1       0   478.3    .045       0   493.3      .1       0
#XS Ineff= 2 , 0
          185.12 1523.14
Permanent Ineff=
       F       F
Bank Sta=478.3,493.3
XS Rating Curve= 0 ,0
Exp/Cntr=0.3,0.1

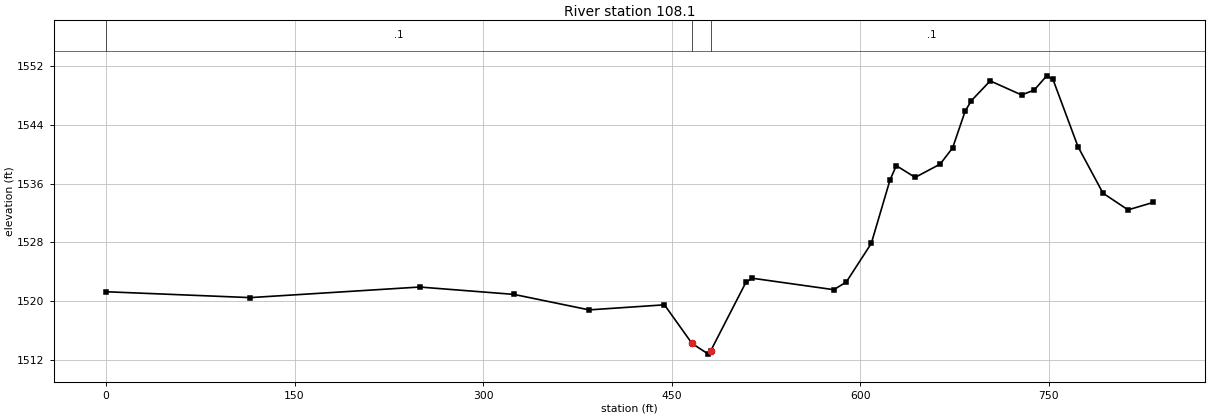
Type RM Length L Ch R = 1 ,108.1   ,113.4,108.1,102.8
XS GIS Cut Line= 3
     1871712.905      210582.512     1872212.164      210681.842
      1872502.31      210538.076
#Sta/Elev= 30
       0 1521.29   114.8 1520.49   249.5 1521.93   324.4 1520.93   384.3 1518.82
   444.2 1519.51   466.1 1514.26   479.1  1512.8   481.1 1513.28     509 1522.57
     514 1523.13   578.8 1521.57   588.8  1522.6   608.7 1527.86   623.6  1536.5
   628.6 1538.45   643.6 1536.85   663.5 1538.66   673.4 1540.87   683.4 1545.88
   688.4 1547.31   703.3 1549.98   728.2 1548.07   738.2 1548.72   748.2 1550.67
   753.2 1550.18   773.1 1541.03     793  1534.7   812.9 1532.43   832.8 1533.44
#Mann= 3 , 0 , 0
       0      .1       0   466.1    .045       0   481.1      .1       0
Bank Sta=466.1,481.1
XS Rating Curve= 0 ,0
Exp/Cntr=0.3,0.1

Chan Stop Cuts=-1
Use User Specified Reach Order=0